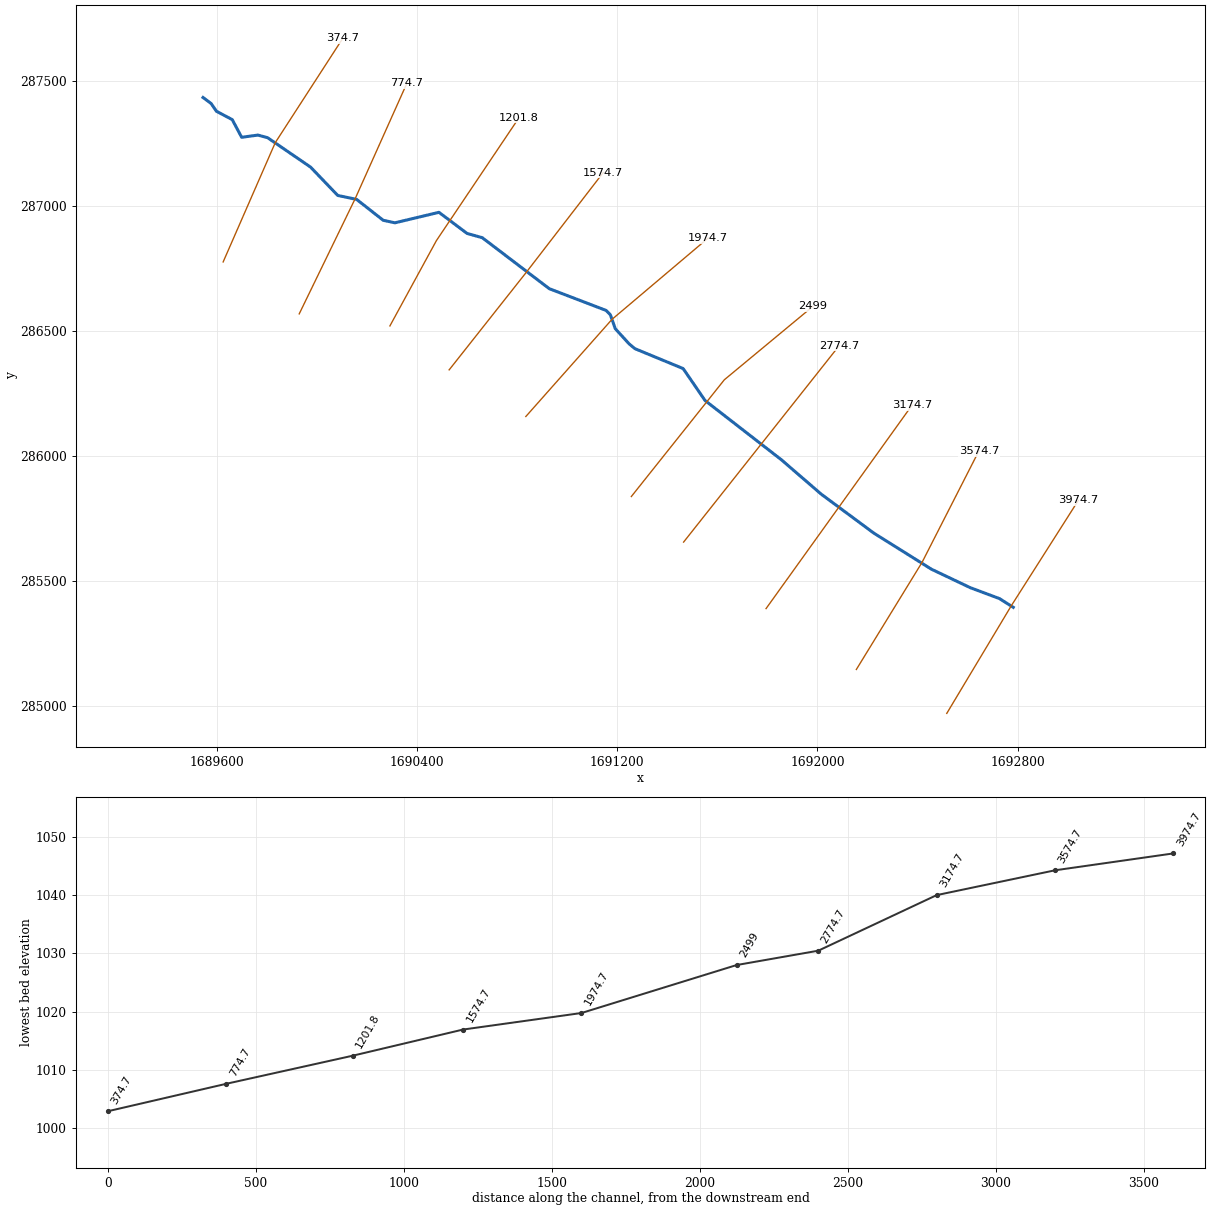
--- TrkyFtRn.prj (project) ---

Proj Title=TrkyFtRn
Current Plan=p01
Geom File=g01
Flow File=f01
Plan File=p01
DSS Export Rating Curves=0
DSS Export Rating Curve Sorted=0
DSS Export Volume Flow Curves=0
DXF OffsetX=0
DXF OffsetY=0
DXF ScaleX=0
DXF ScaleY=0

--- TrkyFtRn.p01 (plan) ---

Plan Title=Floodplain
Program Version=4.00
Geom File=g01
Flow File=f01
K Sum by GR=0
Std Step Tol=0.01
Critical Tol=0.01
Num of Std Step Trials=20
Max Error Tol=0.3
Flow Tol Ratio=0.001
Split Flow NTrial=30
Split Flow Tol=0.02
Split Flow Ratio=0.02
Log Output Level=0
Friction Slope Method=1
Unsteady Friction Slope Method=2
Unsteady Bridges Friction Slope Method=1
Global Log Level=0
CheckData=False
Run HTab=0
Run UNet=0
Run PostProcess=0
UNET Theta=0
UNET Theta Warmup=0
UNET ZTol=0
UNET ZSATol=0
UNET MxIter=0
UNET MaxInSteps=0
UNET DtIC=0
UNET DtMin=0
UNET MaxCRTS=0
UNET WFStab=0
UNET SFStab=0
UNET WFX=0
UNET SFX=0
UNET DSS MLevel=0
UNET DZMax Abort=0
UNET Convert EG Bridges=0
UNET Use Existing IB Tables=0
UNET Froude Limit=0
UNET Froude Power=0
Write IC File=0
Echo Input=False
Echo Output=False
Write Detailed=0

--- TrkyFtRn.f01 (steady flow) ---

Flow Title=NFF Regression Equation
Program Version=4.00
Number of Profiles=1
Profile Names=P100yr
River Rch & RM=TrkyFtRn,Main      ,3974.7
726.2800
River Rch & RM=TrkyFtRn,Main      ,3574.7
739.0180
River Rch & RM=TrkyFtRn,Main      ,1974.7
812.5216
River Rch & RM=TrkyFtRn,Main      ,374.7
881.7333
Boundary for River Rch & Prof#=TrkyFtRn,Main      ,1
Up Type=0
Dn Type=3
Dn Slope=0.011161

--- TrkyFtRn.g01 (geometry) ---

Geom Title=USGS 3m DEM
Program Version=4.00

River Reach=TrkyFtRn     ,Main
Reach XY= 30
     1692781.773      285392.930     1692726.572      285427.972
     1692609.931      285471.650     1692454.892      285545.573
     1692225.451      285689.572     1692015.210      285845.573
     1691855.370      285983.811     1691551.071      286220.490
     1691463.518      286348.362     1691270.900      286428.050
     1691248.229      286446.820     1691192.588      286507.760
     1691172.717      286563.842     1691155.935      286581.066
     1690928.953      286668.062     1690661.345      286872.082
     1690600.404      286889.301     1690488.236      286973.649
     1690312.478      286931.695     1690265.668      286941.852
     1690159.685      287025.314     1690084.173      287041.213
     1689975.538      287154.704     1689804.197      287272.170
     1689765.337      287282.770     1689700.420      287273.936
     1689662.887      287344.591     1689599.738      287378.155
     1689578.540      287409.068     1689546.167      287433.192

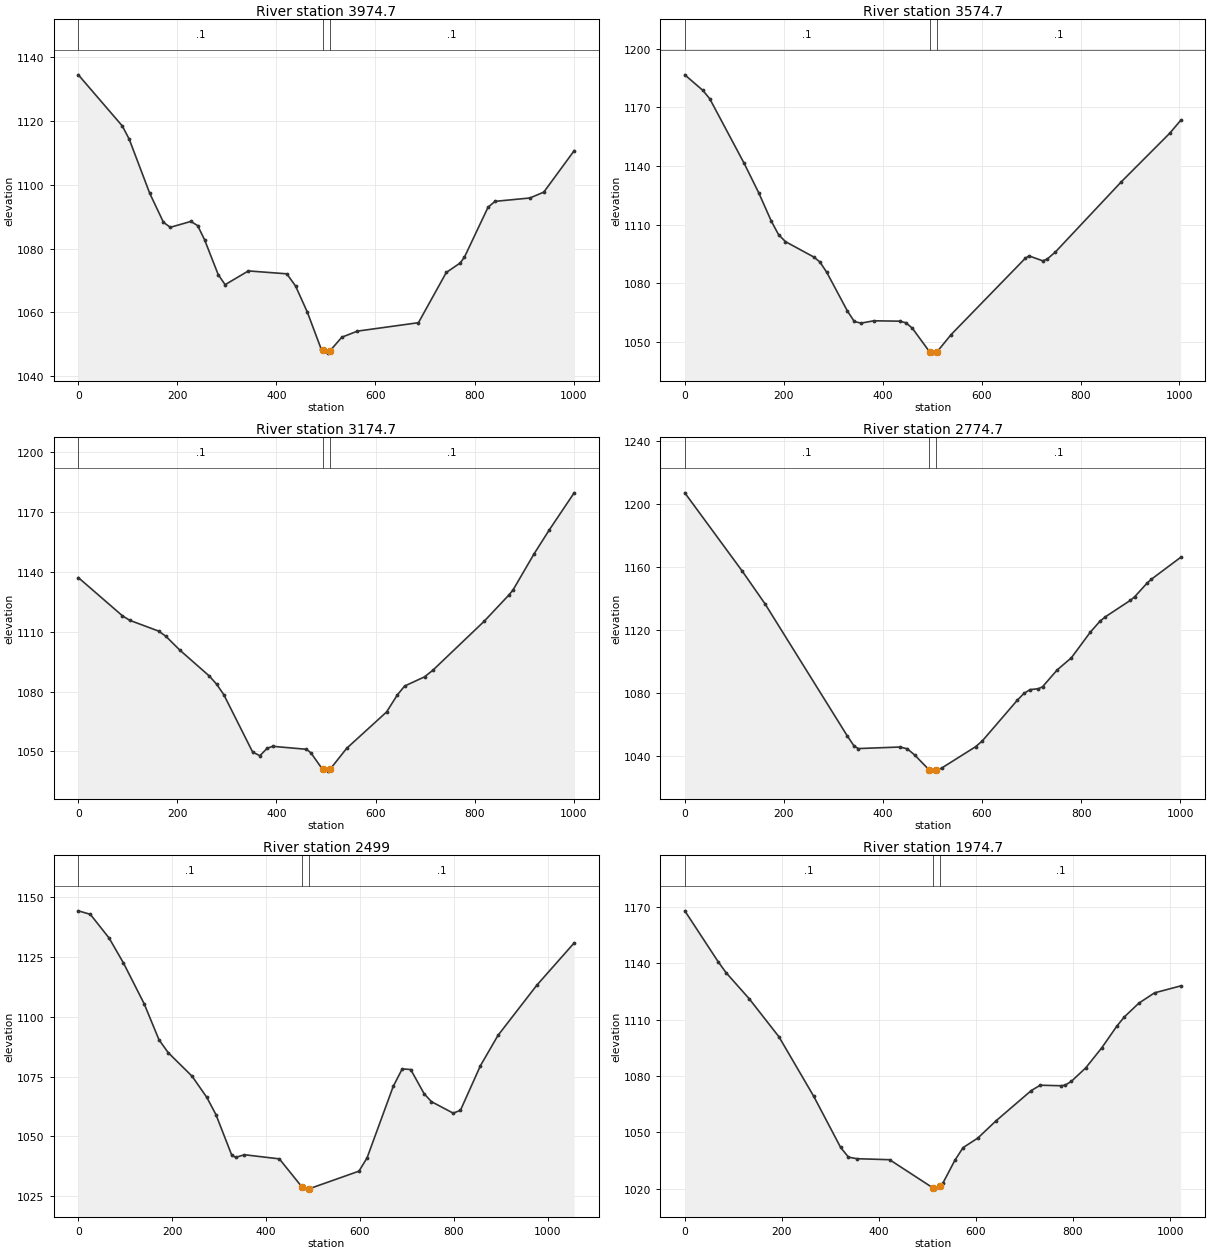
Type RM Length L Ch R = 1 ,3974.7,400.027,400,402.34
XS GIS Cut Line= 3
     1692516.302      284968.579     1692773.331      285398.289
     1693041.547      285820.808
#Sta/Elev= 30
       0 1134.38    88.9 1118.35   102.7 1114.25   144.2 1097.28   171.9 1088.21
   185.7 1086.64   227.2 1088.48   241.0 1087.17   254.9 1082.75   282.5 1071.81
   296.4 1068.68   343.4 1072.99   420.9 1072.08   438.6 1068.28   462.4 1060.09
   490.5 1048.48   493.2 1048.21   503.9 1047.25   508.2 1047.97   532.1 1052.24
   563.7 1054.14   686.8 1056.78   743.0 1072.50   771.1 1075.47   779.7 1077.32
   827.4 1092.95   841.5 1094.77   911.8 1095.82   939.9 1097.66  1001.2 1110.62
#Mann= 3 , 0 , 0
       0     0.1       0   493.2   0.045       0   508.2     0.1       0
Bank Sta=   493.2,   508.2
Exp/Cntr=0.3,0.1

Type RM Length L Ch R = 1 ,3574.7,401.626,400,396.605
XS GIS Cut Line= 3
     1692155.201      285144.332     1692417.493      285572.798
     1692644.405      286018.533
#Sta/Elev= 30
       0 1186.60    36.5 1178.65    50.4 1174.39   120.0 1141.36   149.2 1126.43
   175.1 1111.71   189.6 1104.90   203.5 1101.34   261.4 1093.38   273.1 1090.93
   287.0 1085.65   328.8 1065.85   342.7 1060.52   356.1 1059.67   382.3 1060.87
   434.1 1060.68   447.0 1059.88   460.0 1057.08   494.9 1045.00   502.4 1044.34
   509.9 1044.97   538.5 1053.85   688.6 1092.89   696.0 1094.03   723.9 1091.51
   732.8 1092.45   749.3 1096.06   882.5 1131.92   980.0 1156.64  1002.4 1163.28
#Mann= 3 , 0 , 0
       0     0.1       0   494.9   0.045       0   509.9     0.1       0
Bank Sta=   494.9,   509.9
Exp/Cntr=0.3,0.1

Type RM Length L Ch R = 1 ,3174.7,401.065,400,398.935
XS GIS Cut Line= 3
     1691794.616      285387.937     1692086.047      285794.838
     1692377.479      286201.738
#Sta/Elev= 30
       0 1137.20    89.1 1118.01   103.7 1115.76   162.1 1110.34   176.7 1107.76
   204.5 1100.89   264.4 1087.81   279.0 1083.75   293.6 1078.48   352.0 1049.59
   366.6 1047.81   381.2 1051.51   392.5 1052.51   460.6 1051.02   469.6 1049.21
     493 1040.97   503.2 1040.06     508 1040.92   541.8 1051.52   622.3 1069.75
   644.0 1078.29   658.7 1082.76   698.9 1087.38   715.9 1090.74   819.3 1115.27
   869.0 1128.40   877.4 1130.91   920.1 1149.13   950.7 1161.10  1001.0 1179.74
#Mann= 3 , 0 , 0
       0     0.1       0     493   0.045       0     508     0.1       0
Bank Sta=     493,     508
Exp/Cntr=0.3,0.1

Type RM Length L Ch R = 1 ,2774.7,275.751,275.689,275.626
XS GIS Cut Line= 3
     1691465.376      285654.098     1691775.726      286046.760
     1692086.076      286439.421
#Sta/Elev= 30
       0 1206.87   116.3 1157.11   161.7 1136.65   328.1 1052.77   341.8 1046.39
   350.3 1044.78   434.1 1045.76   449.2 1044.64   464.3 1040.65     493 1031.36
   502.4 1030.48     508 1030.88   519.4 1032.58   587.0 1045.94   600.5 1049.58
   671.5 1075.50   684.7 1079.72   696.9 1082.13   713.8 1082.72   722.2 1083.93
   751.9 1094.67   780.4 1102.30   818.7 1118.56   837.9 1125.40   849.0 1128.28
   899.7 1138.76   908.2 1141.00   933.5 1149.71   942.0 1152.11  1001.0 1165.96
#Mann= 3 , 0 , 0
       0     0.1       0     493   0.045       0     508     0.1       0
Bank Sta=     493,     508
Exp/Cntr=0.3,0.1

Type RM Length L Ch R = 1 ,2499,524.071,524.311,520.623
XS GIS Cut Line= 3
     1691256.643      285836.426     1691627.926      286303.524
     1691981.244      286596.957
#Sta/Elev= 30
       0 1144.16    25.6 1142.69    65.6 1132.77    96.0 1122.44   140.1 1105.42
   171.8 1090.34   191.5 1084.95   242.2 1075.15   273.6 1066.32   293.1 1059.11
   326.7 1042.20   335.2 1041.27   353.8 1042.36   428.1 1040.64   476.2 1028.94
   487.3 1028.01   491.2 1028.13   597.7 1035.51   615.0 1041.09   670.7 1070.92
   689.9 1078.20   707.9 1077.93   736.6 1067.79   752.1 1064.51   798.4 1059.72
   813.8 1060.90   856.5 1079.57   893.7 1092.15   976.5 1113.13  1056.0 1130.76
#Mann= 3 , 0 , 0
       0     0.1       0   476.2   0.045       0   491.2     0.1       0
Bank Sta=   476.2,   491.2
Exp/Cntr=0.3,0.1

Type RM Length L Ch R = 1 ,1974.7,399.66,400,404.537
XS GIS Cut Line= 3
     1690835.323      286156.610     1691179.304      286545.251
     1691562.893      286870.314
#Sta/Elev= 30
       0 1167.97    69.1 1140.73    85.0 1135.05   132.5 1121.21   194.0 1100.89
   265.6 1069.24   321.2 1041.92   337.3 1036.77   354.5 1035.95   422.1 1035.41
   511.5 1020.37   516.4 1019.74   526.5 1021.34   531.5 1022.74   556.7 1035.17
   573.6 1041.87   603.9 1046.95   641.2 1056.08   714.1 1072.26   732.5 1075.09
   775.8 1074.80   784.2 1075.16   796.9 1077.21   826.3 1084.34   859.1 1094.94
   890.2 1106.49   905.8 1111.47   935.8 1118.81   968.1 1124.29  1021.8 1127.97
#Mann= 3 , 0 , 0
       0     0.1       0   511.5   0.045       0   526.5     0.1       0
Bank Sta=   511.5,   526.5
Exp/Cntr=0.3,0.1

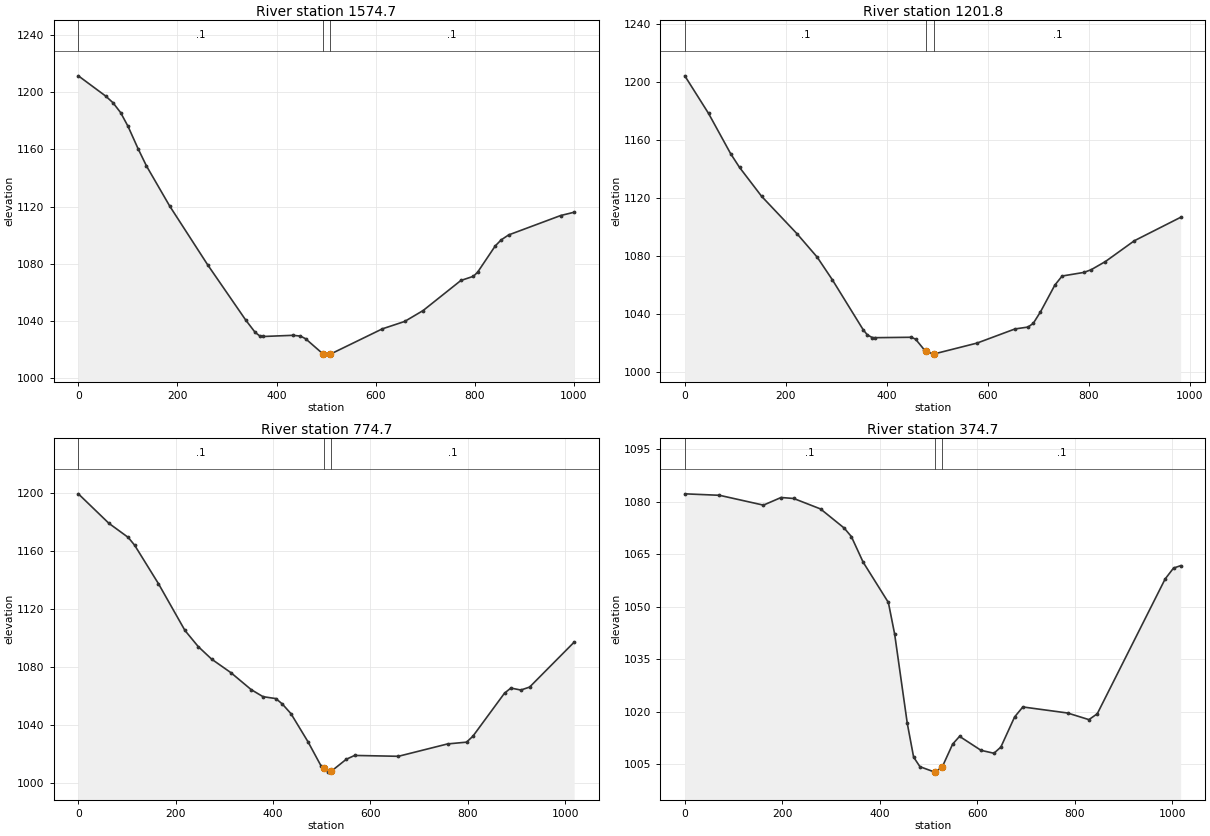
Type RM Length L Ch R = 1 ,1574.7,371.218,372.929,374.372
XS GIS Cut Line= 3
     1690529.139      286343.253     1690839.131      286736.188
     1691144.443      287132.834
#Sta/Elev= 30
       0 1211.38    55.0 1197.28    69.8 1192.63    85.3 1185.70   100.4 1175.99
   120.5 1160.49   137.4 1148.45   184.3 1120.39   261.0 1079.28   337.7 1040.72
   356.9 1032.03   365.6 1029.75   372.6 1029.21   433.1 1030.04   448.2 1029.49
   458.6 1027.63     493 1017.22     508 1016.91   508.6 1016.89   613.5 1034.57
   658.4 1039.72   695.6 1047.34   771.8 1068.35   797.2 1071.29   805.7 1074.19
   841.2 1092.51   853.2 1096.74   868.2 1100.19   973.1 1113.74  1000.4 1116.06
#Mann= 3 , 0 , 0
       0     0.1       0     493   0.045       0     508     0.1       0
Bank Sta=     493,     508
Exp/Cntr=0.3,0.1

Type RM Length L Ch R = 1 ,1201.8,423.911,427.071,430.928
XS GIS Cut Line= 3
     1690292.505      286519.107     1690478.147      286860.448
     1690808.443      287353.037
#Sta/Elev= 30
       0 1204.02    47.0 1178.14    90.8 1150.39   108.3 1140.99   152.1 1121.04
   222.1 1095.30   262.1 1079.16   292.2 1063.53   353.4 1029.04   361.5 1025.61
   370.9 1023.83   376.1 1023.70   448.3 1023.99   456.9 1022.68   474.0 1015.42
   478.4 1014.50   491.1 1012.38   493.4 1012.50   578.5 1019.98   653.7 1029.72
   679.4 1031.02   689.8 1033.55   704.1 1041.45   732.7 1059.97   747.0 1066.16
   789.9 1068.64   804.2 1070.45   832.8 1076.16   890.0 1090.46   981.6 1106.59
#Mann= 3 , 0 , 0
       0     0.1       0   478.4   0.045       0   493.4     0.1       0
Bank Sta=   478.4,   493.4
Exp/Cntr=0.3,0.1

Type RM Length L Ch R = 1 ,774.7,399.14,400,396.483
XS GIS Cut Line= 3
     1689930.399      286567.393     1690153.594      287027.852
     1690360.511      287490.671
#Sta/Elev= 30
       0 1199.14    62.8 1178.84   102.4 1169.16   115.6 1163.80   164.6 1137.28
   219.0 1105.09   246.2 1094.02   273.9 1085.32   313.5 1076.00   355.1 1064.34
   379.4 1059.49   405.8 1058.17   419.0 1054.47   436.8 1047.80   471.8 1028.45
   498.2 1012.08   504.2 1010.35   513.7 1007.54   519.2 1008.03   550.4 1016.38
   567.6 1019.03   657.5 1018.44   758.5 1026.95   797.5 1028.18   810.5 1032.23
   875.5 1061.89   888.5 1065.41   909.1 1064.07   927.1 1066.10  1018.6 1097.03
#Mann= 3 , 0 , 0
       0     0.1       0   504.2   0.045       0   519.2     0.1       0
Bank Sta=   504.2,   519.2
Exp/Cntr=0.3,0.1

Type RM Length L Ch R = 1 ,374.7,380.338,374.685,371.614
XS GIS Cut Line= 3
     1689626.573      286775.213     1689834.710      287252.468
     1690104.275      287669.942
#Sta/Elev= 30
       0 1082.32    71.2 1081.90   161.4 1079.09   197.6 1081.27   223.5 1080.99
   278.6 1078.00   327.1 1072.54   341.8 1070.12   366.0 1062.80   417.8 1051.28
   430.7 1042.24   456.6 1016.75   469.6 1007.11   482.6 1004.36   513.1 1002.81
   513.2 1002.81   528.2 1004.24   549.7 1010.81   563.9 1013.03   607.9 1009.04
   634.5 1008.20   648.7 1009.98   676.9 1018.58   693.8 1021.43   785.6 1019.70
   829.4 1017.81   846.5 1019.48   985.8 1057.99  1003.0 1061.10  1017.6 1061.79
#Mann= 3 , 0 , 0
       0     0.1       0   513.2   0.045       0   528.2     0.1       0
Bank Sta=   513.2,   528.2
Exp/Cntr=0.3,0.1